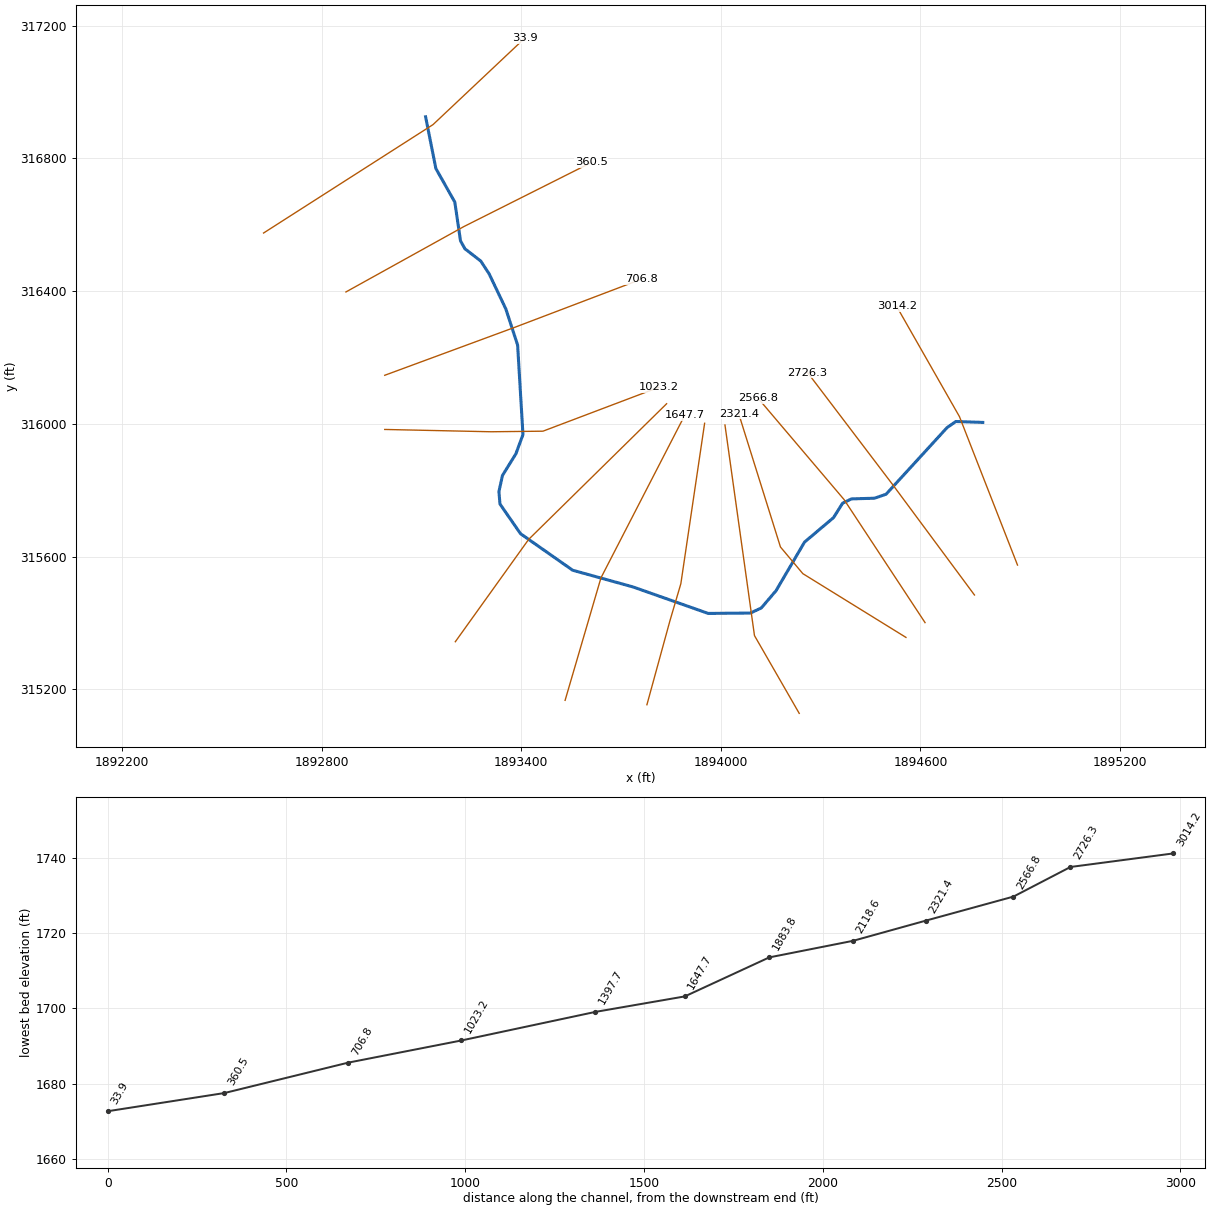
--- LFLISNDYCK.prj (project) ---

Proj Title=LFLISNDYCK
Current Plan=p01
Default Exp/Contr=0,0
English Units
Geom File=g01
Flow File=f01
Plan File=p01
BEGIN DESCRIPTION:
END DESCRIPTION:
DSS Export Rating Curves= 0
DSS Export Rating Curve Sorted= 0
DSS Export Volume Flow Curves= 0
DXF OffsetX= 0
DXF OffsetY= 0
DXF ScaleX= 0
DXF ScaleY= 0

--- LFLISNDYCK.p01 (plan) ---

Plan Title=Floodplain
Program Version=4.00
Geom File=g01
Flow File=f01
K Sum by GR=0
Std Step Tol=0.01
Critical Tol=0.01
Num of Std Step Trials=20
Max Error Tol=0.3
Flow Tol Ratio=0.001
Split Flow NTrial=30
Split Flow Tol=0.02
Split Flow Ratio=0.02
Log Output Level=0
Friction Slope Method=1
Unsteady Friction Slope Method=2
Unsteady Bridges Friction Slope Method=1
Global Log Level=0
CheckData=False
Run HTab=0
Run UNet=0
Run PostProcess=0
UNET Theta=0
UNET Theta Warmup=0
UNET ZTol=0
UNET ZSATol=0
UNET MxIter=0
UNET MaxInSteps=0
UNET DtIC=0
UNET DtMin=0
UNET MaxCRTS=0
UNET WFStab=0
UNET SFStab=0
UNET WFX=0
UNET SFX=0
UNET DSS MLevel=0
UNET DZMax Abort=0
UNET Convert EG Bridges=0
UNET Use Existing IB Tables=0
UNET Froude Limit=0
UNET Froude Power=0
Write IC File=0
Echo Input=False
Echo Output=False
Write Detailed=0

--- LFLISNDYCK.f01 (steady flow) ---

Flow Title=NFF Regression Equation
Program Version=4.10
Number of Profiles= 1
Profile Names=P100yr
River Rch & RM=LFLISNDYCK,Main            ,3014.2
553.4656
River Rch & RM=LFLISNDYCK,Main            ,1647.7
565.1411
River Rch & RM=LFLISNDYCK,Main            ,1397.7
652.1248
River Rch & RM=LFLISNDYCK,Main            ,33.9
665.5844
Boundary for River Rch & Prof#=LFLISNDYCK,Main            , 1
Up Type= 0
Dn Type= 1
Dn Known WS=1678.52
DSS Import GetInterval= 0
DSS Import GetPeak= 0
DSS Import FillOption= 0

--- LFLISNDYCK.g01 (geometry) ---

Geom Title=USGS 10m DEM
Program Version=4.10

River Reach=LFLISNDYCK      ,Main
Reach XY= 30
     1894787.282      316004.334     1894706.205      316007.044
     1894679.755      315988.529      1894496.65      315788.034
     1894461.813      315775.926     1894392.483      315773.928
     1894365.917      315761.003      1894338.55      315717.417
     1894251.424      315643.719     1894165.703      315497.235
     1894121.216      315445.152     1894088.664      315429.961
      1893961.71      315428.876      1893735.49      315508.726
     1893554.307      315558.981     1893397.497      315669.101
     1893335.659      315758.533     1893332.633      315796.254
     1893343.221      315844.457     1893383.705      315909.973
      1893404.85      315967.665     1893388.794      316237.252
     1893353.287      316346.398     1893303.032      316452.198
     1893277.904      316490.551     1893230.294      316527.581
     1893217.069      316551.386     1893199.992      316668.025
     1893143.009      316769.334     1893112.101      316925.186

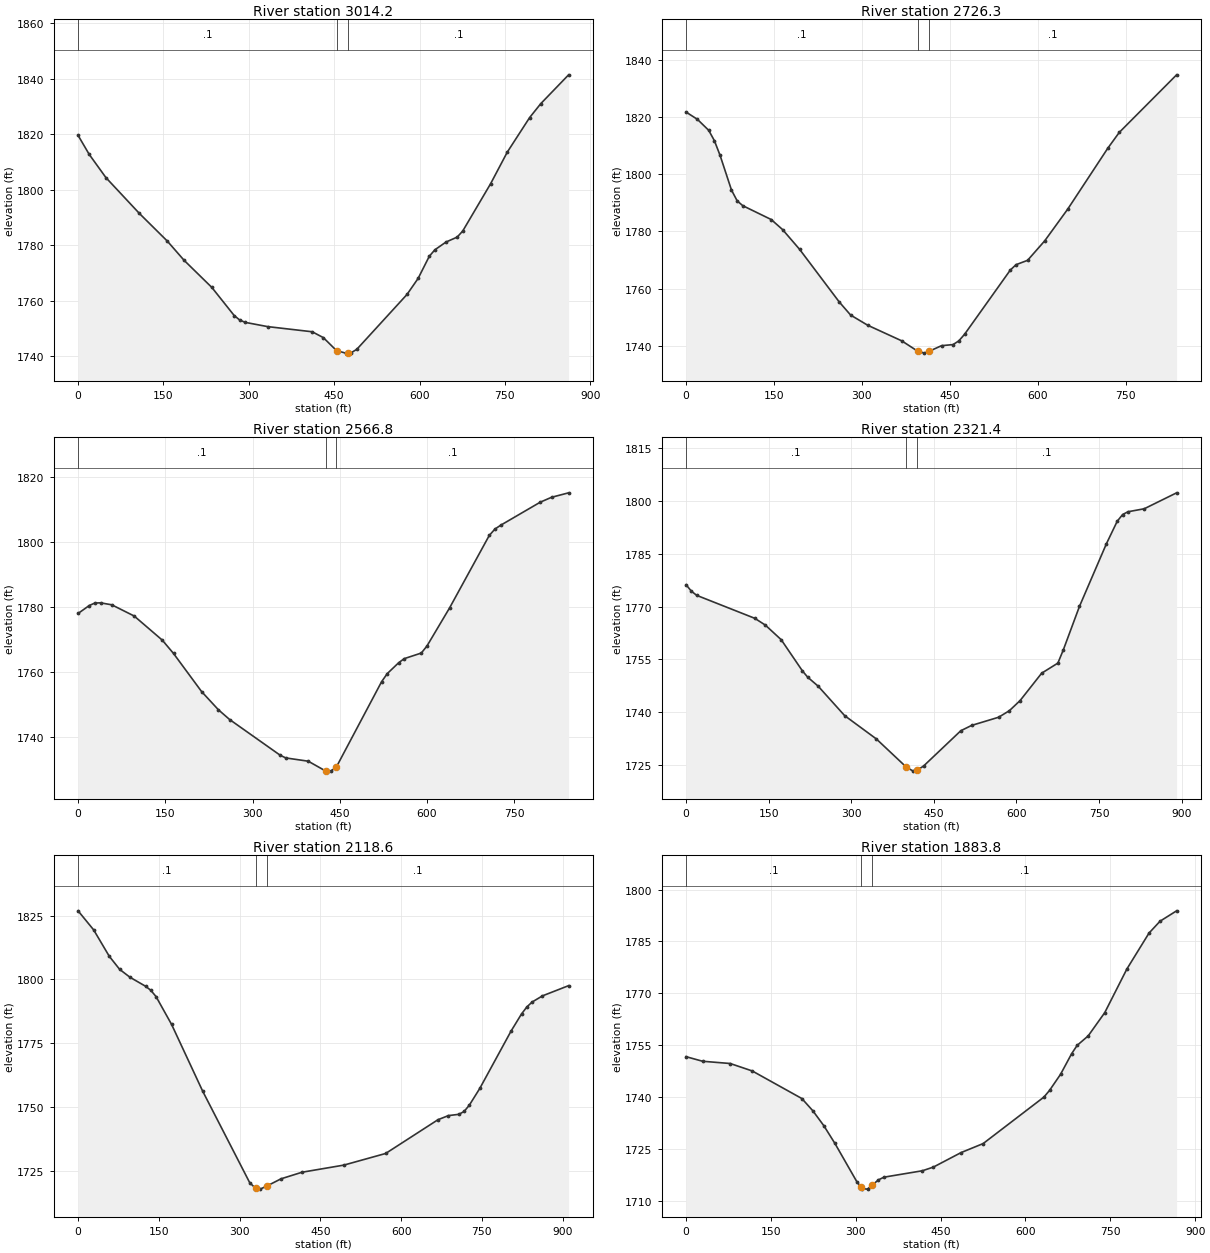
Type RM Length L Ch R = 1 ,3014.2  ,281.5,287.9,293.1
XS GIS Cut Line= 3
     1894891.735       315574.57     1894717.223      316021.801
     1894528.421      316353.832
#Sta/Elev= 30
       0 1819.54    19.6 1812.68      49 1804.31   107.8 1791.41   156.8 1781.47
   186.2 1774.57   235.1 1764.77   274.3 1754.67   284.1 1753.03   293.9 1752.19
   333.1 1750.67   411.5 1748.81   431.1 1746.69   454.2 1742.03   470.3 1741.12
   474.2 1741.18   480.1 1741.28   489.9 1742.51     578 1762.24   597.6 1768.04
   617.2    1776     627 1778.33   646.6 1781.13   666.2  1782.9     676 1785.11
   724.9 1802.11   754.3 1813.52   793.5 1825.94   813.1 1830.96     862 1841.34
#Mann= 3 , 0 , 0
       0      .1       0   454.2    .045       0   474.2      .1       0
Bank Sta=454.2,474.2
XS Rating Curve= 0 ,0
Exp/Cntr=0.3,0.1

Type RM Length L Ch R = 1 ,2726.3  ,160.7,159.5,159.8
XS GIS Cut Line= 3
     1894762.316      315484.373      1894514.74      315819.143
     1894260.666      316154.414
#Sta/Elev= 30
       0  1821.7    19.4 1819.15    38.7 1815.31    48.4 1811.67    58.1 1806.53
    77.5 1794.46    87.2 1790.69    96.8    1789   145.2 1784.18   164.6 1780.68
   193.7 1773.77   261.4 1755.38   280.8 1750.81   309.9 1747.26     368 1741.81
   395.2  1738.2   406.7 1737.52   415.2 1738.21   435.9 1740.12   455.5  1740.5
   465.3 1741.78   475.1 1744.07   553.3 1766.54   563.1 1768.41   582.7 1769.92
     612 1776.74   651.2  1787.8   719.6 1809.07   739.2  1814.6     837  1834.7
#Mann= 3 , 0 , 0
       0      .1       0   395.2    .045       0   415.2      .1       0
Bank Sta=395.2,415.2
XS Rating Curve= 0 ,0
Exp/Cntr=0.3,0.1

Type RM Length L Ch R = 1 ,2566.8  ,242.1,245.4,245.3
XS GIS Cut Line= 3
     1894613.774       315401.13        1894370.      315772.235
      1894111.85      316077.073
#Sta/Elev= 30
       0 1778.11    19.3 1780.56      29 1781.33    38.6 1781.38    57.9 1780.78
    96.5 1777.33   144.8 1769.92   164.1 1765.83   212.4 1754.11   241.3 1748.52
   260.6 1745.52   347.5 1734.55   357.1 1733.72   395.8 1732.71   425.6 1729.71
   434.4 1729.66     444 1730.87     522 1757.16   531.7 1759.63   551.2 1762.96
   560.9 1764.23   590.2 1765.95   599.9  1768.1   638.9 1779.84   707.1  1802.1
   716.8 1804.05   726.6 1805.22   794.8 1812.32   814.2 1813.82   843.5 1815.19
#Mann= 3 , 0 , 0
       0      .1       0   425.6    .045       0     444      .1       0
Bank Sta=425.6,444
XS Rating Curve= 0 ,0
Exp/Cntr=0.3,0.1

Type RM Length L Ch R = 1 ,2321.4  ,216.9,202.8,189.6
XS GIS Cut Line= 4
     1894556.353      315356.616     1894246.302      315548.711
     1894179.028      315629.006     1894053.324      316031.092
#Sta/Elev= 30
       0 1776.21     9.6 1774.39    19.2  1773.2   124.8 1766.67     144 1764.74
   172.8 1760.59   211.2 1751.76   220.8 1749.96     240 1747.38     288 1739.03
   345.5 1732.42   400.1 1724.39   412.4 1723.27   420.1 1723.57   431.4 1724.73
   498.9 1734.74   518.5 1736.25   567.5 1738.57     587 1740.42   606.6 1743.31
   645.8 1751.09   675.2 1753.95     685 1757.67   714.4 1770.06   763.4 1787.87
     783 1794.25   792.8 1796.15   802.6 1796.94     832 1797.78   890.8 1802.31
#Mann= 3 , 0 , 0
       0      .1       0   400.1    .045       0   420.1      .1       0
Bank Sta=400.1,420.1
XS Rating Curve= 0 ,0
Exp/Cntr=0.3,0.1

Type RM Length L Ch R = 1 ,2118.6  ,245.4,234.8,224.2
XS GIS Cut Line= 3
     1894235.452      315127.704     1894100.903      315362.079
     1894012.207      315996.693
#Sta/Elev= 30
       0 1826.83      29 1819.36    57.9 1809.06    77.2 1803.93    96.5 1800.82
   125.5  1797.3   135.1 1795.72   144.8 1793.28   173.7 1782.37   231.6 1756.18
   318.8 1720.44     330 1718.18   338.2 1717.93     350 1719.08     377 1721.97
   415.9 1724.54   493.6 1727.33   571.2 1731.88   668.3 1745.08   687.7  1746.7
   707.2  1747.2   716.9 1748.32   726.6 1750.77     746 1757.32   804.2  1779.8
   823.6 1786.49   833.4  1789.2   843.1 1791.12   862.5 1793.56     911 1797.55
#Mann= 3 , 0 , 0
       0      .1       0     330    .045       0     350      .1       0
Bank Sta=330,350
XS Rating Curve= 0 ,0
Exp/Cntr=0.3,0.1

Type RM Length L Ch R = 1 ,1883.8  ,236,236.1,231.4
XS GIS Cut Line= 4
     1893777.552      315153.745     1893846.997      315407.652
     1893879.549      315518.329     1893951.018      316001.703
#Sta/Elev= 30
       0 1751.75    29.2 1750.43      78 1749.78     117 1747.63   204.7 1739.67
   224.2 1736.12   243.7 1731.79   263.2  1726.7   301.7 1715.72   308.8 1714.19
   311.3 1713.65   320.9 1713.52   328.8 1714.66   340.1 1716.19   349.8 1716.97
   417.7 1718.82   437.2 1719.88   486.1 1724.06   525.2 1726.67   632.7  1740.1
   642.5    1742     662 1746.65   681.6  1752.6   691.3    1755   710.9 1757.75
   740.2 1764.47   779.3 1777.06   818.4 1787.42   837.9 1790.85   867.2 1793.85
#Mann= 3 , 0 , 0
       0      .1       0   308.8    .045       0   328.8      .1       0
Bank Sta=308.8,328.8
XS Rating Curve= 0 ,0
Exp/Cntr=0.3,0.1

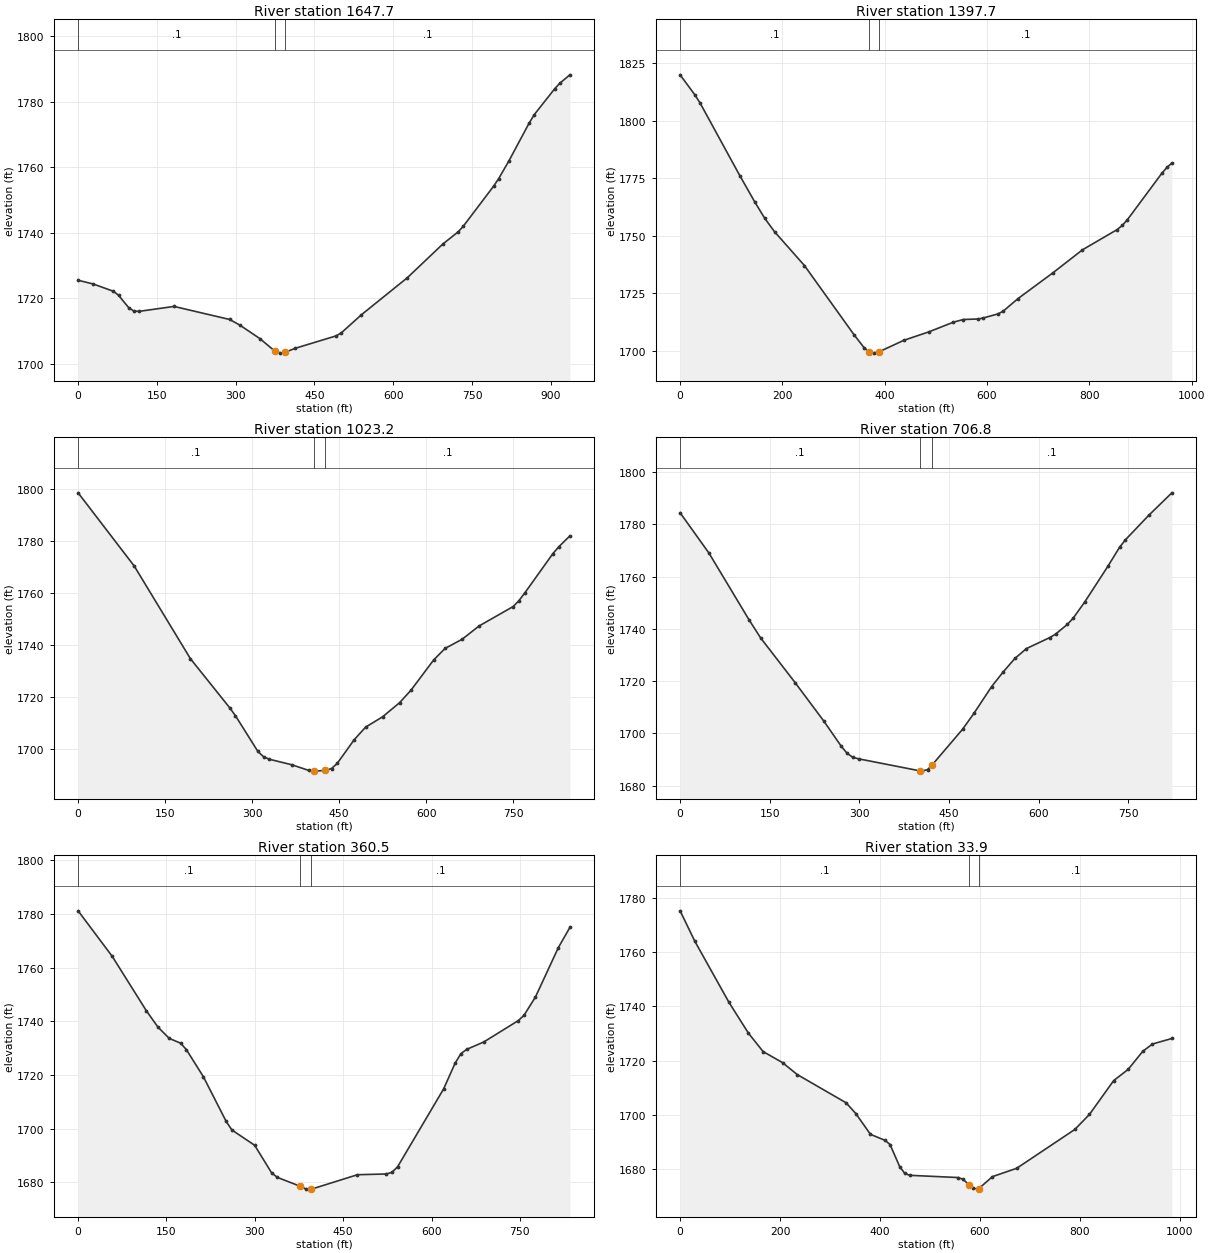
Type RM Length L Ch R = 1 ,1647.7  ,258.5,250,241.9
XS GIS Cut Line= 3
     1893531.566      315167.006     1893639.369       315536.08
     1893891.725      316026.798
#Sta/Elev= 30
       0 1725.42    28.8 1724.28    67.3 1722.05    76.9 1720.84    96.1 1717.09
   105.7 1716.06   115.4 1715.91   182.6 1717.43   288.4 1713.45   307.6 1711.76
     346 1707.61   374.5 1703.79   384.5 1703.17   394.5 1703.45   413.5 1704.65
     491 1708.43   500.7  1709.3   539.4 1714.89   626.5 1726.15   694.3 1736.47
   723.3 1740.16     733 1741.85   791.1 1754.15   800.8 1756.48   820.1 1761.84
   858.8 1773.43   868.5    1776   907.3 1783.88   916.9 1785.55   936.3 1788.15
#Mann= 3 , 0 , 0
       0      .1       0   374.5    .045       0   394.5      .1       0
Bank Sta=374.5,394.5
XS Rating Curve= 0 ,0
Exp/Cntr=0.3,0.1

Type RM Length L Ch R = 1 ,1397.7  ,397.8,374.6,354.8
XS GIS Cut Line= 3
     1893201.531      315343.583     1893421.994      315651.886
     1893836.756      316060.627
#Sta/Elev= 30
       0 1820.07    29.2 1811.26    38.9 1807.87   116.6 1776.28   145.8 1764.86
   165.2 1757.76   184.6 1751.85     243 1737.16   340.2    1707   359.6 1701.44
     369 1699.65     379 1699.06     389 1699.65   437.2 1704.62   485.8 1708.27
   534.3 1712.52   553.7 1713.68   582.8 1713.91   592.5 1714.34   621.6 1716.13
   631.4 1717.28   660.5 1722.77   728.4 1733.92   786.6 1743.99   854.6 1752.81
   864.3 1754.57     874 1756.96   941.9 1777.32   951.6 1779.79   961.3 1781.71
#Mann= 3 , 0 , 0
       0      .1       0     369    .045       0     389      .1       0
Bank Sta=369,389
XS Rating Curve= 0 ,0
Exp/Cntr=0.3,0.1

Type RM Length L Ch R = 1 ,1023.2  ,307.4,316.4,324.8
XS GIS Cut Line= 4
     1892989.271      315983.129     1893308.716      315976.185
     1893464.966      315977.921     1893812.542      316109.823
#Sta/Elev= 30
       0 1798.47    96.8 1770.29   193.6 1734.68   261.4 1715.79   271.1  1712.8
   309.8 1699.05   319.5 1697.02   329.3 1696.06   368.4 1693.92   397.6 1691.74
   406.2 1691.51   407.4 1691.48   426.2 1691.75   436.7 1692.48   446.5 1694.44
   475.8 1703.56   495.4 1708.38   524.7 1712.36     554 1717.79   573.6 1722.58
   612.7 1734.21   632.3 1738.64   661.7 1742.16     691 1747.28   749.7 1754.75
   759.5 1756.96   769.3 1759.83   818.2 1775.09     828 1777.64   847.5 1781.91
#Mann= 3 , 0 , 0
       0      .1       0   406.2    .045       0   426.2      .1       0
Bank Sta=406.2,426.2
XS Rating Curve= 0 ,0
Exp/Cntr=0.3,0.1

Type RM Length L Ch R = 1 ,706.8   ,342.6,346.3,350
XS GIS Cut Line= 3
     1892989.233      316146.308     1893377.768      316289.914
     1893759.661      316435.399
#Sta/Elev= 30
       0 1784.41    48.2 1769.02   115.6 1743.38   134.9  1736.5   192.7 1719.38
   240.8 1704.64   269.7  1695.1   279.4 1692.44     289 1690.88   298.6 1690.31
   401.5  1685.7   404.6  1685.6   414.2 1686.21   421.5 1687.91   472.6 1701.59
   492.1 1707.84   521.3 1717.95   540.7 1723.55   560.2 1728.69   579.6 1732.48
   618.6 1736.68   628.3    1738   647.8 1741.68   657.5 1744.03   676.9 1750.22
   715.9 1763.97   735.3 1771.18     745 1774.03     784 1783.39   822.9 1792.04
#Mann= 3 , 0 , 0
       0      .1       0   401.5    .045       0   421.5      .1       0
Bank Sta=401.5,421.5
XS Rating Curve= 0 ,0
Exp/Cntr=0.3,0.1

Type RM Length L Ch R = 1 ,360.5   ,323.5,326.6,329.9
XS GIS Cut Line= 3
     1892872.603        316397.4     1893227.584      316594.612
     1893610.613      316787.504
#Sta/Elev= 30
       0 1781.22      58 1764.22     116 1743.94   135.4 1737.94   154.7 1733.69
     174 1731.91   183.7 1729.53   212.7 1719.39   251.4 1702.74     261 1699.58
   299.7 1693.87   328.7 1683.53   338.4 1681.89   376.2 1678.67   386.8 1677.58
   396.2 1677.53   474.3  1682.9     523 1683.17   532.8 1683.77   542.5  1685.9
   620.5 1714.86     640 1724.43   649.8 1727.98   659.5 1729.58   688.7 1732.36
   747.2  1740.3     757 1742.28   776.5 1749.14   815.4 1767.55   834.9 1775.03
#Mann= 3 , 0 , 0
       0      .1       0   376.2    .045       0   396.2      .1       0
Bank Sta=376.2,396.2
XS Rating Curve= 0 ,0
Exp/Cntr=0.3,0.1

Type RM Length L Ch R = 1 ,33.9    ,43.8,33.9,23
XS GIS Cut Line= 3
        1892625.         316575.     1893134.631      316901.762
     1893409.686      317161.536
#Sta/Elev= 30
       0 1775.14    29.3 1763.99    97.6 1741.49   136.7  1730.1     166 1723.34
     205 1719.25   234.3 1714.87     332 1704.49   351.5 1700.51   380.8 1692.86
   410.1 1690.65   419.9 1689.12   439.4 1680.92   449.2 1678.54   458.9 1677.79
   556.6 1676.96   566.3 1676.28   577.7 1674.34   585.9 1673.07   595.6  1672.7
   597.7 1672.93   624.8  1677.3   673.3 1680.37   789.7 1694.68   818.8  1700.2
   867.3 1712.65   896.4  1716.8   925.5 1723.43   944.9 1726.11   983.7 1728.16
#Mann= 3 , 0 , 0
       0      .1       0   577.7    .045       0   597.7      .1       0
Bank Sta=577.7,597.7
XS Rating Curve= 0 ,0
Exp/Cntr=0.3,0.1

Chan Stop Cuts=-1
Use User Specified Reach Order=0
Composite Channel Slope=5